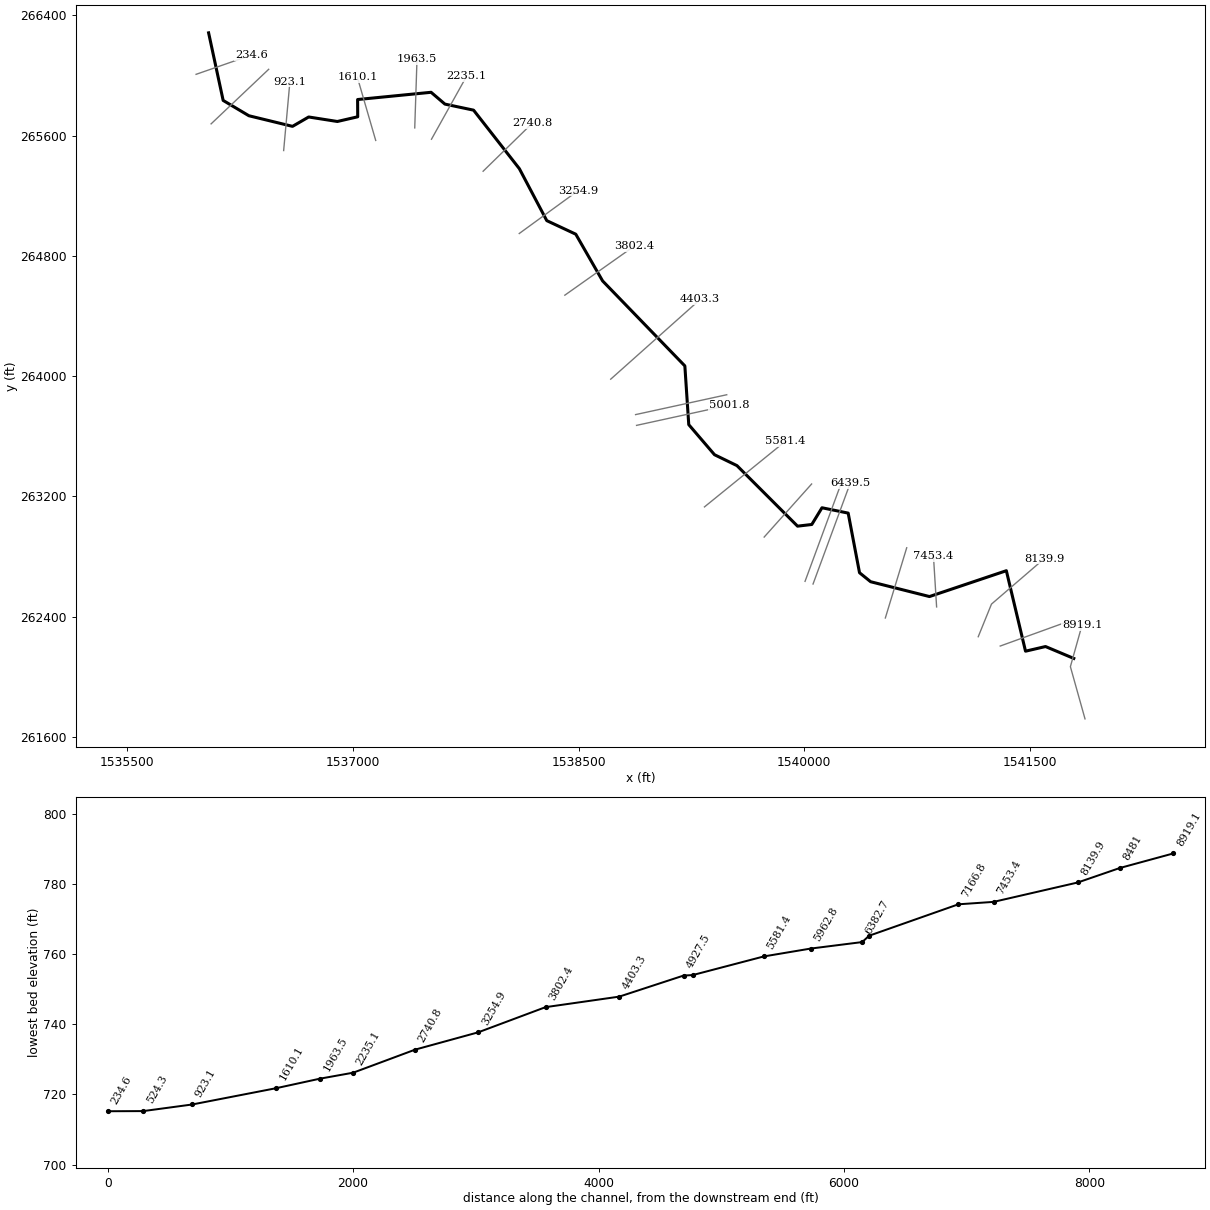
--- RCKCMPRN.prj (project) ---

Proj Title=RCKCMPRN
Current Plan=p01
Default Exp/Contr=0,0
English Units
Geom File=g01
Flow File=f01
Plan File=p01
BEGIN DESCRIPTION:
END DESCRIPTION:
DSS Export Rating Curves= 0
DSS Export Rating Curve Sorted= 0
DSS Export Volume Flow Curves= 0
DXF OffsetX= 0
DXF OffsetY= 0
DXF ScaleX= 0
DXF ScaleY= 0

--- RCKCMPRN.p01 (plan) ---

Plan Title=Floodplain
Program Version=4.00
Geom File=g01
Flow File=f01
K Sum by GR=0
Std Step Tol=0.01
Critical Tol=0.01
Num of Std Step Trials=20
Max Error Tol=0.3
Flow Tol Ratio=0.001
Split Flow NTrial=30
Split Flow Tol=0.02
Split Flow Ratio=0.02
Log Output Level=0
Friction Slope Method=1
Unsteady Friction Slope Method=2
Unsteady Bridges Friction Slope Method=1
Global Log Level=0
CheckData=False
Run HTab=0
Run UNet=0
Run PostProcess=0
UNET Theta=0
UNET Theta Warmup=0
UNET ZTol=0
UNET ZSATol=0
UNET MxIter=0
UNET MaxInSteps=0
UNET DtIC=0
UNET DtMin=0
UNET MaxCRTS=0
UNET WFStab=0
UNET SFStab=0
UNET WFX=0
UNET SFX=0
UNET DSS MLevel=0
UNET DZMax Abort=0
UNET Convert EG Bridges=0
UNET Use Existing IB Tables=0
UNET Froude Limit=0
UNET Froude Power=0
Write IC File=0
Echo Input=False
Echo Output=False
Write Detailed=0

--- RCKCMPRN.f01 (steady flow) ---

Flow Title=NFF Regression Equation
Program Version=4.00
Number of Profiles=1
Profile Names=P100yr
River Rch & RM=RCKCMPRN,Main      ,8919.1
905.4175
River Rch & RM=RCKCMPRN,Main      ,7453.4
938.3414
River Rch & RM=RCKCMPRN,Main      ,5962.8
1018.281
River Rch & RM=RCKCMPRN,Main      ,4403.3
1129.009
River Rch & RM=RCKCMPRN,Main      ,3802.4
1204.740
River Rch & RM=RCKCMPRN,Main      ,524.3
1288.080
River Rch & RM=RCKCMPRN,Main      ,234.6
1289.631
Boundary for River Rch & Prof#=RCKCMPRN,Main      ,1
Up Type=0
Dn Type=3
Dn Slope=0.003875

--- RCKCMPRN.g01 (geometry) ---

Geom Title=USGS 10m DEM
Program Version=4.10

River Reach=RCKCMPRN        ,Main
Reach XY= 30
     1541792.918       262123.04     1541604.885      262202.089
     1541471.962      262171.159     1541344.398      262706.376
     1540833.287      262534.501     1540441.968      262633.112
     1540368.057      262692.954     1540292.662      263089.363
     1540118.457      263124.924     1540050.743      263013.763
     1539955.969      263002.596     1539553.152      263405.093
      1539403.83      263477.653     1539232.593      263677.557
     1539206.621      264068.184      1538659.65      264633.378
     1538481.299      264944.044     1538288.495      265034.154
     1538106.204       265379.64      1537801.69      265768.876
     1537611.065      265809.154     1537519.167      265887.673
      1537030.54      265839.533     1537031.204      265724.779
     1536895.787      265693.529     1536705.182      265723.467
     1536597.769      265661.169     1536307.593      265731.723
     1536136.502      265833.548     1536039.674      266283.053

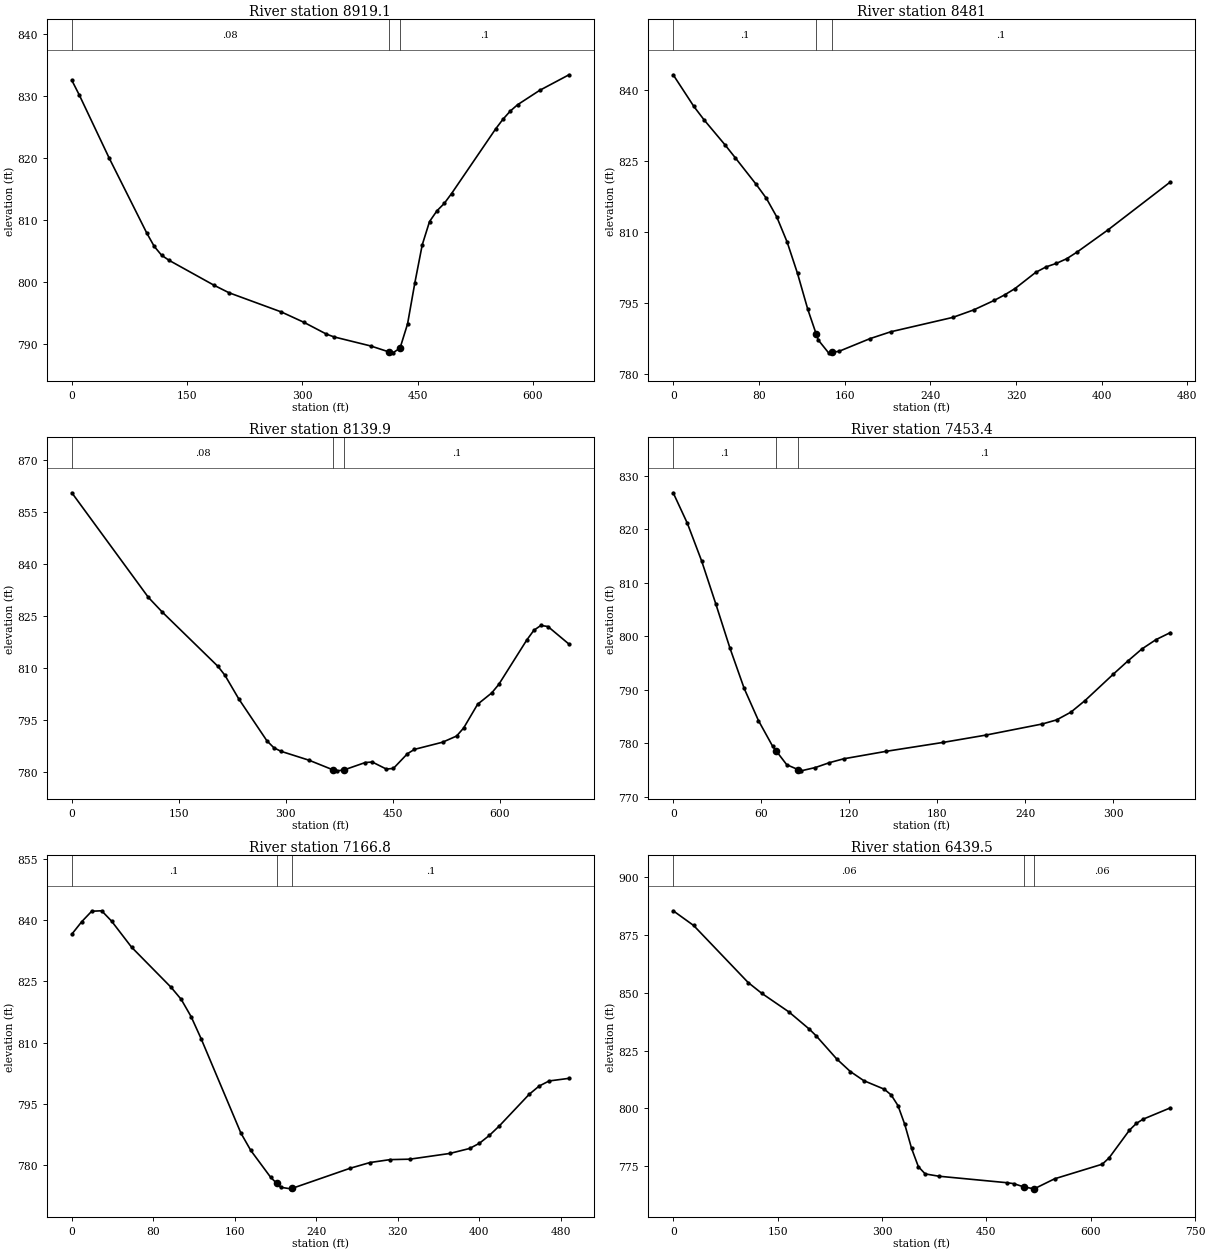
Type RM Length L Ch R = 1 ,8919.1  ,458.4,438.1,415.7
XS GIS Cut Line= 3
     1541867.513      261721.076     1541770.291      262068.299
     1541847.664      262344.171
#Sta/Elev= 30
       0  832.51     9.8  830.12    48.7  819.97    97.4  807.96   107.2  805.79
   116.9  804.35   126.7  803.53   185.2  799.52   204.6  798.32   272.9  795.22
   302.1  793.56   331.3  791.67   341.1  791.22   389.2  789.75   412.2  788.82
   417.9  788.65   427.2  789.41     437  793.31   446.5  799.93   456.1  806.03
   465.6  809.78   475.2   811.5   484.7  812.69   494.3  814.29   551.6  824.68
   561.1  826.23   570.7  827.56   580.2  828.58   608.9  830.89   647.1   833.4
#Mann= 3 , 0 , 0
       0     .08       0   412.2    .045       0   427.2      .1       0
Bank Sta=412.2,427.2
XS Rating Curve= 0 ,0
Exp/Cntr=0.3,0.1

Type RM Length L Ch R = 1 ,8481    ,330.7,341.1,408.6
XS GIS Cut Line= 2
     1541303.686      262205.414      1541740.23      262363.358
#Sta/Elev= 30
       0  843.16    19.3  836.48      29   833.6    48.4  828.37      58  825.64
    77.4  820.06      87  817.09    96.7  813.17   106.4  807.86   116.1  801.23
   125.7  793.65   133.4  788.54   135.4  787.21   145.1  784.48   148.4  784.59
   154.8   784.8   183.8  787.48   203.1  788.92   261.1  791.96   280.5  793.53
   299.8  795.55   309.5  796.71   319.2  798.05   338.5  801.46   348.2  802.62
   357.8  803.36   367.5  804.35   377.2  805.76   406.2  810.46   464.2  820.54
#Mann= 3 , 0 , 0
       0      .1       0   133.4    .045       0   148.4      .1       0
Bank Sta=133.4,148.4
XS Rating Curve= 0 ,0
Exp/Cntr=0.3,0.1

Type RM Length L Ch R = 1 ,8139.9  ,621.9,686.5,636.1
XS GIS Cut Line= 3
     1541157.479      262267.337     1541245.479      262484.191
     1541595.943      262786.079
#Sta/Elev= 30
       0  860.54   107.3  830.37   126.8  826.13   204.8  810.48   214.5  807.93
     234  801.08   273.4  789.01   283.2  787.01   293.1     786   332.4  783.43
   366.2  780.63   371.8  780.37   381.2  780.62   411.2  782.77     421  782.91
   440.7  780.88   450.6  781.07   470.2   785.3   480.1  786.56   519.4  788.62
   539.1   790.4     549  792.72   568.6  799.57   588.3  802.82   598.2  805.28
   637.5   818.1   647.4  820.89   657.2  822.29   667.1  821.98   696.6  816.91
#Mann= 3 , 0 , 0
       0     .08       0   366.2    .045       0   381.2      .1       0
Bank Sta=366.2,381.2
XS Rating Curve= 0 ,0
Exp/Cntr=0.3,0.1

Type RM Length L Ch R = 1 ,7453.4  ,294.1,286.7,278.5
XS GIS Cut Line= 2
     1540880.717      262465.559     1540859.746      262803.675
#Sta/Elev= 27
       0   826.8     9.7  821.07    19.4  814.05      29  806.07    38.7  797.76
    48.4  790.23    58.1  784.24    67.8  779.42    70.3  778.52    77.4  775.98
    85.3  775.05    87.1  774.84    96.8  775.45   106.5  776.37   116.2  777.09
   145.2  778.49   183.9  780.15   212.9  781.51   251.6   783.6   261.3  784.36
     271   785.8   280.7  787.98     300  792.92   309.7  795.33   319.4  797.61
   329.1  799.37   338.8  800.67
#Mann= 3 , 0 , 0
       0      .1       0    70.3    .045       0    85.3      .1       0
Bank Sta=70.3,85.3
XS Rating Curve= 0 ,0
Exp/Cntr=0.3,0.1

Type RM Length L Ch R = 1 ,7166.8  ,725.7,727.2,726
XS GIS Cut Line= 2
     1540539.793      262391.995      1540681.88      262858.945
#Sta/Elev= 30
       0  836.57     9.8  839.65    19.5  842.19    29.3   842.3      39  839.77
    58.6  833.39    97.6   823.5   107.4  820.58   117.1  816.36   126.9  810.97
     166  787.81   175.7  783.56   195.2  776.98     201  775.54     205  774.54
   214.8  774.15     216  774.24   273.3   779.2   292.8   780.6   312.4  781.31
   331.9  781.42     371  782.82   390.5  784.04   400.2  785.32     410  787.26
   419.8  789.59     449  797.31   458.8  799.34   468.6  800.59   488.1  801.23
#Mann= 3 , 0 , 0
       0      .1       0     201    .045       0     216      .1       0
Bank Sta=201,216
XS Rating Curve= 0 ,0
Exp/Cntr=0.3,0.1

Type RM Length L Ch R = 1 ,6439.5  ,56.4,56.8,56.4
XS GIS Cut Line= 2
     1540059.036      262617.807     1540306.121      263288.173
#Sta/Elev= 30
       0  885.42    29.4  879.06   107.7  854.41   127.2  849.75   166.4  841.67
   195.7  834.23   205.5  831.34   234.9  821.39   254.5  815.93     274  811.96
   303.4  808.27   313.2  805.81     323   801.2   332.8  793.04   342.6  782.65
   352.3   774.8   362.1  771.66   381.7  770.66   479.6  767.85   489.4  767.44
   503.8  766.04   518.7   765.2   518.8  765.21   548.1  769.54   616.6  775.86
   626.4  778.58   655.7  790.58   665.5  793.47   675.3  795.32   714.4  800.21
#Mann= 3 , 0 , 0
       0     .06       0   503.8    .045       0   518.8     .06       0
Bank Sta=503.8,518.8
XS Rating Curve= 0 ,0
Exp/Cntr=0.3,0.1

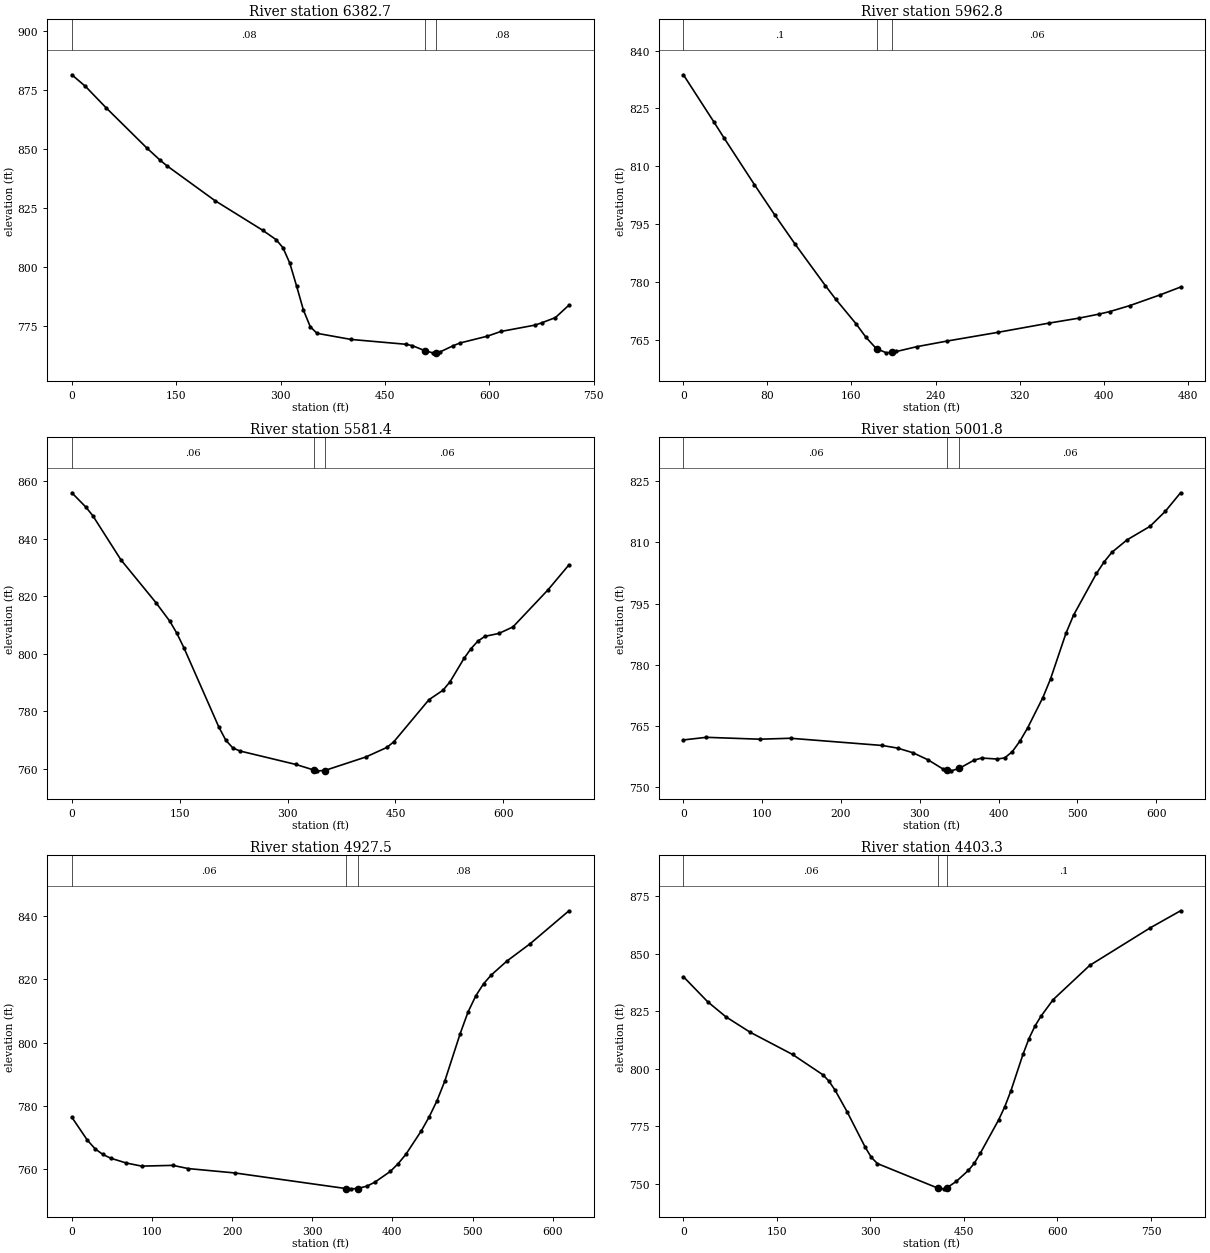
Type RM Length L Ch R = 1 ,6382.7  ,428.2,419.9,411.1
XS GIS Cut Line= 2
     1540005.876      262635.642     1540252.961      263306.007
#Sta/Elev= 30
       0  881.52    19.6  876.59    48.9   867.6   107.7  850.44   127.2  845.14
     137  842.78   205.5  828.09     274  815.51   293.6  811.46   303.4  808.06
   313.2  801.49     323  791.74   332.8  781.55   342.6   774.5   352.3  771.68
   401.3  769.08   479.6  767.04   489.4  766.45   507.7  764.25   518.7  763.39
   522.7  763.51   528.5  763.69   548.1  766.43   557.9  767.58     597  770.46
   616.6  772.47   665.5  775.17   675.3  776.15   694.9  778.36   714.4  783.67
#Mann= 3 , 0 , 0
       0     .08       0   507.7    .045       0   522.7     .08       0
Bank Sta=507.7,522.7
XS Rating Curve= 0 ,0
Exp/Cntr=0.3,0.1

Type RM Length L Ch R = 1 ,5962.8  ,384.5,381.4,377.3
XS GIS Cut Line= 2
     1539734.064      262930.091     1540049.504      263282.972
#Sta/Elev= 25
       0   833.7      29  821.46    38.6  817.34    67.6  805.19    86.9  797.35
   106.2   789.8   135.2  778.96   144.9  775.49   164.2  769.13   173.9  765.54
   183.5  762.68     184  762.62   193.2  761.54     199  761.75   202.8  761.89
   222.2  763.14   251.2  764.61   299.4  766.86   347.7  769.24   376.7  770.55
     396  771.61   405.7  772.23     425   773.8     454   776.6   473.3  778.61
#Mann= 3 , 0 , 0
       0      .1       0     184    .045       0     199     .06       0
Bank Sta=184,199
XS Rating Curve= 0 ,0
Exp/Cntr=0.3,0.1

Type RM Length L Ch R = 1 ,5581.4  ,589.9,579.6,568.4
XS GIS Cut Line= 2
     1539337.006      263130.571     1539873.811      263566.003
#Sta/Elev= 30
       0  856.01    19.5  851.04    29.2  848.02    68.2  832.71   116.8  817.84
   136.3  811.31     146  807.14   155.8  802.12   204.4  774.52   214.2  769.89
   223.9  767.26   233.6  766.21   311.5  761.52   336.5  759.58   340.7   759.3
   351.5   759.4   408.9  764.13   438.1  767.45   447.8  769.44   496.5  784.04
     516  787.33   525.7  790.23   545.2  798.38   554.9  801.77   564.6  804.44
   574.4  806.08   593.8  807.09   613.3  809.35     662  822.24   691.2  830.95
#Mann= 3 , 0 , 0
       0     .06       0   336.5    .045       0   351.5     .06       0
Bank Sta=336.5,351.5
XS Rating Curve= 0 ,0
Exp/Cntr=0.3,0.1

Type RM Length L Ch R = 1 ,5001.8  ,73.7,74.3,75
XS GIS Cut Line= 2
     1538885.506      263672.792     1539501.825       263807.34
#Sta/Elev= 30
       0  761.57    29.1  762.21      97  761.75   135.9  761.98   252.3  760.21
   271.7  759.57   291.2  758.43   310.6  756.67     330  754.36   334.9  754.17
   339.7  753.99   349.9  754.58   368.8  756.61   378.5  757.13   397.9  756.89
   407.6  757.15   417.3  758.69     427  761.28   436.7   764.5   456.1  771.97
   465.8  776.52   485.3  787.68     495  792.16   524.1   802.4   533.8  805.23
   543.5  807.56   562.9  810.64     592  813.95   611.4  817.63   630.8  822.19
#Mann= 3 , 0 , 0
       0     .06       0   334.9    .045       0   349.9     .06       0
Bank Sta=334.9,349.9
XS Rating Curve= 0 ,0
Exp/Cntr=0.3,0.1

Type RM Length L Ch R = 1 ,4927.5  ,512.1,524.2,534.2
XS GIS Cut Line= 2
     1538878.995      263744.406     1539485.115      263876.485
#Sta/Elev= 30
       0  776.45    19.4   769.2    29.1  766.47    38.8  764.69    48.5  763.52
    67.8  762.01    87.2  761.02     126  761.26   145.4  760.24   203.6  758.86
   341.7  753.95   348.9  753.85   356.7  753.95   368.3  754.71     378  755.94
   397.4  759.35   407.1  761.78   416.8  764.75   436.2  772.21   445.9  776.58
   455.6  781.65   465.3  787.83   484.6  802.88   494.3  809.63     504  814.75
   513.7  818.58   523.4  821.36   542.8  825.74   571.9  831.23   620.3  841.62
#Mann= 3 , 0 , 0
       0     .06       0   341.7    .045       0   356.7     .08       0
Bank Sta=341.7,356.7
XS Rating Curve= 0 ,0
Exp/Cntr=0.3,0.1

Type RM Length L Ch R = 1 ,4403.3  ,602.7,600.9,597.6
XS GIS Cut Line= 2
     1538713.602      263979.979     1539308.864      264510.628
#Sta/Elev= 30
       0  840.07    38.9  829.18    68.1  822.64     107  815.94     175  806.27
   223.7  797.44   233.4  794.68   243.1  790.82   262.6  781.34   291.8  765.84
   301.5   761.5   311.2  758.83   408.3  748.14   418.2  747.85   423.3  748.43
   437.6  751.06   457.1  755.88   466.8  759.04   476.5  763.48   505.7  777.87
   515.4  783.51   525.2  790.39   544.6  806.28   554.3  813.19     564  818.68
   573.8  823.03   593.2  830.14   651.6  844.96   748.8  861.32   797.4  868.73
#Mann= 3 , 0 , 0
       0     .06       0   408.3    .045       0   423.3      .1       0
Bank Sta=408.3,423.3
XS Rating Curve= 0 ,0
Exp/Cntr=0.3,0.1

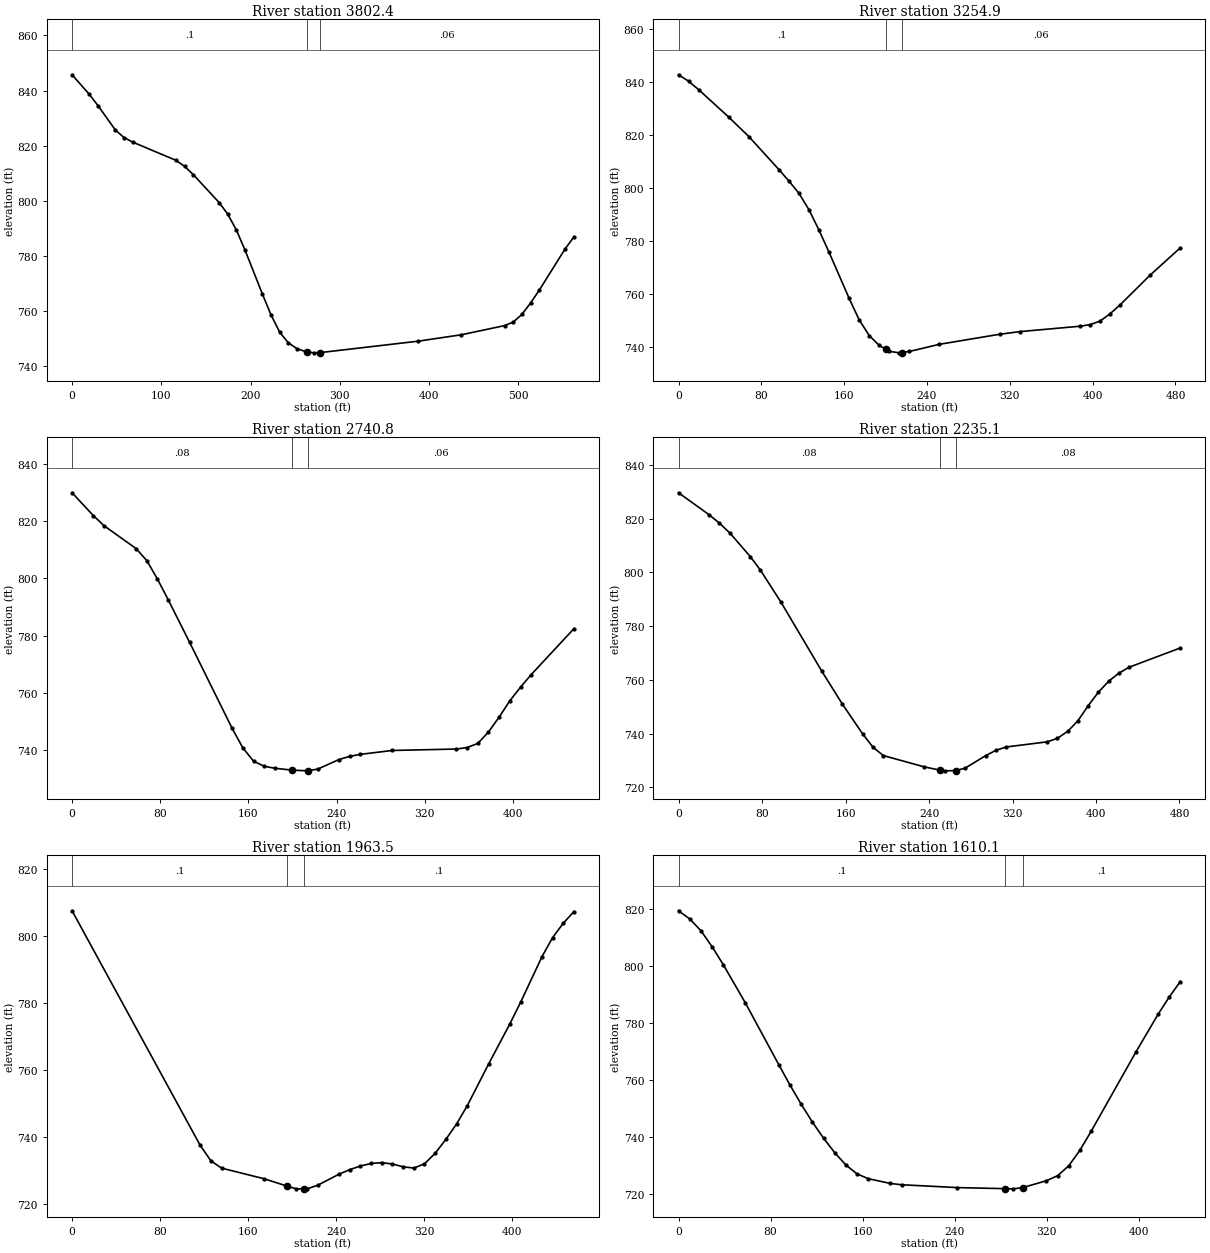
Type RM Length L Ch R = 1 ,3802.4  ,547.2,547.5,547.2
XS GIS Cut Line= 2
     1538408.596      264538.555     1538867.853      264863.187
#Sta/Elev= 30
       0  845.73    19.4  838.61    29.1   834.5    48.5  825.71    58.2  822.95
    67.9  821.31   116.4   814.7   126.1  812.51   135.8  809.54   164.8  799.38
   174.5  795.16   184.2  789.38   193.9  782.08   213.3  766.21     223   758.6
   232.7  752.35   242.4  748.48   252.1  746.36   262.9  745.17   271.5  744.85
   277.9  744.93   387.9  749.08   436.4  751.41   484.8  754.73   494.5  756.02
   504.2   758.8   513.9  762.94   523.6  767.57   552.7  782.62   562.4  786.88
#Mann= 3 , 0 , 0
       0      .1       0   262.9    .045       0   277.9     .06       0
Bank Sta=262.9,277.9
XS Rating Curve= 0 ,0
Exp/Cntr=0.3,0.1

Type RM Length L Ch R = 1 ,3254.9  ,510.4,514.1,518.1
XS GIS Cut Line= 2
     1538105.362      264948.606     1538497.214      265233.914
#Sta/Elev= 30
       0  842.57     9.7  840.14    19.4  836.98    48.5  826.59    67.9  819.28
    96.9  806.84   106.6  802.51   116.3  797.88     126  791.66   135.7  783.96
   145.4  775.61   164.8  758.23   174.5  750.14   184.2  744.22   193.9  740.48
   200.4  738.99   203.6  738.26   213.3  737.69   215.4   737.8     223  738.21
     252  740.91   310.2   744.7   329.6  745.69   387.8  747.73   397.5  748.32
   407.2  749.67   416.8  752.41   426.6  755.82   455.6  767.02   484.7  777.31
#Mann= 3 , 0 , 0
       0      .1       0   200.4    .045       0   215.4     .06       0
Bank Sta=200.4,215.4
XS Rating Curve= 0 ,0
Exp/Cntr=0.3,0.1

Type RM Length L Ch R = 1 ,2740.8  ,498.9,505.7,510.7
XS GIS Cut Line= 2
     1537865.153      265362.762     1538190.956      265680.961
#Sta/Elev= 30
       0  829.94    19.4  821.94    29.1   818.4    58.1  810.44    67.8  806.25
    77.5  799.79    87.2  792.58   106.6  777.73   145.3  747.58     155  740.78
   164.7  736.13   174.4  734.35   184.1  733.66   199.5  733.02   213.2  732.76
   214.5  732.84   222.9  733.36   242.2   736.7   251.9  737.82   261.6  738.52
   290.7  739.88   348.8  740.38   358.5   740.9   368.2  742.33   377.9  746.33
   387.6  751.55   397.3  757.24     407     762   416.6  766.36   455.4  782.42
#Mann= 3 , 0 , 0
       0     .08       0   199.5    .045       0   214.5     .06       0
Bank Sta=199.5,214.5
XS Rating Curve= 0 ,0
Exp/Cntr=0.3,0.1

Type RM Length L Ch R = 1 ,2235.1  ,260.3,271.6,283.6
XS GIS Cut Line= 2
     1537521.778      265575.586     1537755.846      265995.561
#Sta/Elev= 30
       0   829.6    29.4  821.41    39.2   818.3    49.1  814.67    68.7   805.9
    78.5   800.8    98.1  788.96   137.4  763.16     157  750.98   176.6  739.82
   186.4  734.94   196.2  731.86   235.5  727.65   250.7  726.42   255.1  726.18
   265.7  726.28   274.7   727.2   294.4  731.87   304.2  733.82     314  735.06
   353.2  736.96     363  738.27   372.9  740.87   382.7  744.81   392.5   750.4
   402.3  755.42   412.1   759.5   421.9   762.5   431.7  764.71   480.8  771.89
#Mann= 3 , 0 , 0
       0     .08       0   250.7    .045       0   265.7     .08       0
Bank Sta=250.7,265.7
XS Rating Curve= 0 ,0
Exp/Cntr=0.3,0.1

Type RM Length L Ch R = 1 ,1963.5  ,345.4,353.5,359.1
XS GIS Cut Line= 2
      1537410.46      265650.783     1537425.461       266106.39
#Sta/Elev= 30
       0  807.53   116.4  737.45   126.1  732.84   135.8  730.66   174.6  727.47
   195.4  725.27   203.7  724.47   210.4  724.47   213.4  724.47   223.1  725.54
   242.5  728.85   252.2  730.21   261.9  731.28   271.6  732.04   281.3   732.3
     291  731.89   300.7  731.06   310.4  730.67   320.1  731.94   329.8  735.08
   339.5  739.22   349.2  743.83   358.9  749.25   378.3  761.72   397.7  773.76
   407.4  780.18   426.8  793.79   436.5  799.52   446.2  803.83   455.8  807.26
#Mann= 3 , 0 , 0
       0      .1       0   195.4    .045       0   210.4      .1       0
Bank Sta=195.4,210.4
XS Rating Curve= 0 ,0
Exp/Cntr=0.3,0.1

Type RM Length L Ch R = 1 ,1610.1  ,691.2,686.9,676.4
XS GIS Cut Line= 2
     1537150.899      265567.519       1537029.3      265986.213
#Sta/Elev= 30
       0  819.43     9.7  816.58    19.4  812.46    29.1  806.84    38.8  800.56
    58.1  787.05    87.2  765.31    96.9   758.2   106.6  751.46   116.3  745.23
     126  739.58   135.6  734.53   145.3   730.2     155  727.05   164.7  725.37
   184.1  723.67   193.8  723.22   242.2  722.22   283.9  721.84   290.7  721.78
   298.9  722.19   319.7  724.64   329.4   726.4   339.1  729.88   348.8  735.36
   358.5  741.97   397.2  769.69   416.6  783.03   426.3  789.12     436  794.58
#Mann= 3 , 0 , 0
       0      .1       0   283.9    .045       0   298.9      .1       0
Bank Sta=283.9,298.9
XS Rating Curve= 0 ,0
Exp/Cntr=0.3,0.1

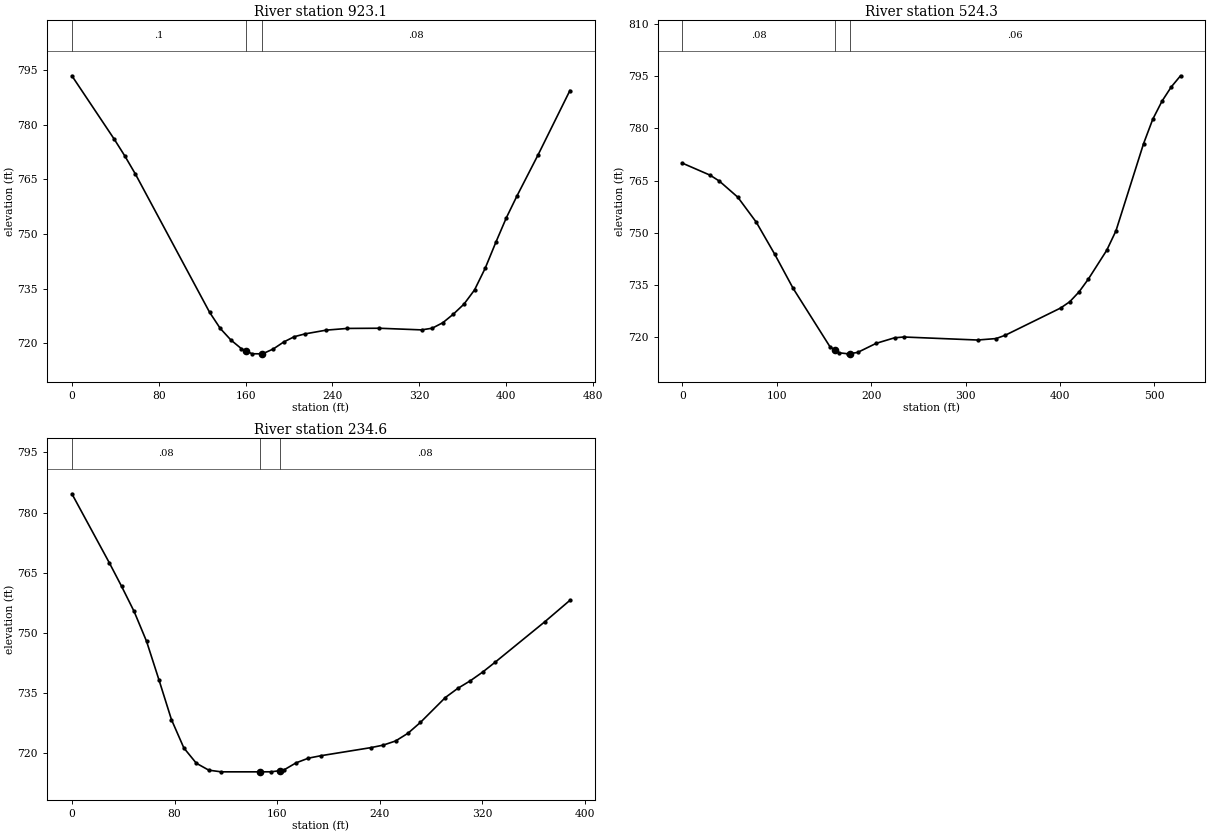
Type RM Length L Ch R = 1 ,923.1   ,415.1,398.9,382.3
XS GIS Cut Line= 2
     1536538.775      265500.286     1536580.247      265957.333
#Sta/Elev= 30
       0  793.38    39.1  775.96    48.8  771.38    58.6  766.39   126.9  728.51
   136.7  724.09   146.5  720.92   156.2  718.53   160.6  717.91     166  717.14
   175.6  717.12   185.5  718.44   195.3  720.39     205  721.83   214.8  722.59
   234.3  723.62   253.9  724.09   283.2  724.14   322.2  723.69     332  724.15
   341.8  725.66   351.5  728.01   361.3  730.76     371  734.64   380.8  740.58
   390.6  747.68   400.3  754.43   410.1  760.42   429.6  771.72   458.9  789.34
#Mann= 3 , 0 , 0
       0      .1       0   160.6    .045       0   175.6     .08       0
Bank Sta=160.6,175.6
XS Rating Curve= 0 ,0
Exp/Cntr=0.3,0.1

Type RM Length L Ch R = 1 ,524.3   ,299.1,289.7,280
XS GIS Cut Line= 2
     1536056.245      265677.669     1536439.206      266040.513
#Sta/Elev= 30
       0  770.03    29.3  766.58    39.1  764.88    58.6  760.26    78.2  753.07
    97.7  743.88   117.2  734.07   156.3  717.26   162.1  716.24   166.1  715.53
   175.8  715.24   177.1  715.29   185.6  715.65   205.2  718.26   224.7  719.85
   234.5  720.08   312.6  719.21   332.2  719.63   341.9  720.58   400.6  728.41
   410.3  730.22   420.1  733.04   429.9   736.7   449.4  744.98   459.2  750.58
   488.5  775.68   498.2  782.66     508  787.86   517.8  791.95   527.6  795.15
#Mann= 3 , 0 , 0
       0     .08       0   162.1    .045       0   177.1     .06       0
Bank Sta=162.1,177.1
XS Rating Curve= 0 ,0
Exp/Cntr=0.3,0.1

Type RM Length L Ch R = 1 ,234.6   ,234.4,234.6,235
XS GIS Cut Line= 2
     1535956.392      266007.098     1536322.956      266134.751
#Sta/Elev= 30
       0  784.68    29.1  767.48    38.8  761.52    48.5  755.28    58.2  747.82
    67.9  738.16    77.6  728.26    87.3  721.16      97  717.35   106.7  715.62
   116.4   715.2     147   715.2   155.3  715.21     162  715.49     165  715.62
   174.7  717.44   184.4  718.62   194.1  719.23   232.9  721.24   242.6  721.87
   252.3  722.91     262  724.85   271.7  727.56   291.1  733.77   300.8  736.06
   310.5  737.94   320.2  740.13   329.9  742.59   368.8  752.75   388.2  758.06
#Mann= 3 , 0 , 0
       0     .08       0     147    .045       0     162     .08       0
Bank Sta=147,162
XS Rating Curve= 0 ,0
Exp/Cntr=0.3,0.1

Chan Stop Cuts=-1
Use User Specified Reach Order=0
Composite Channel Slope=5